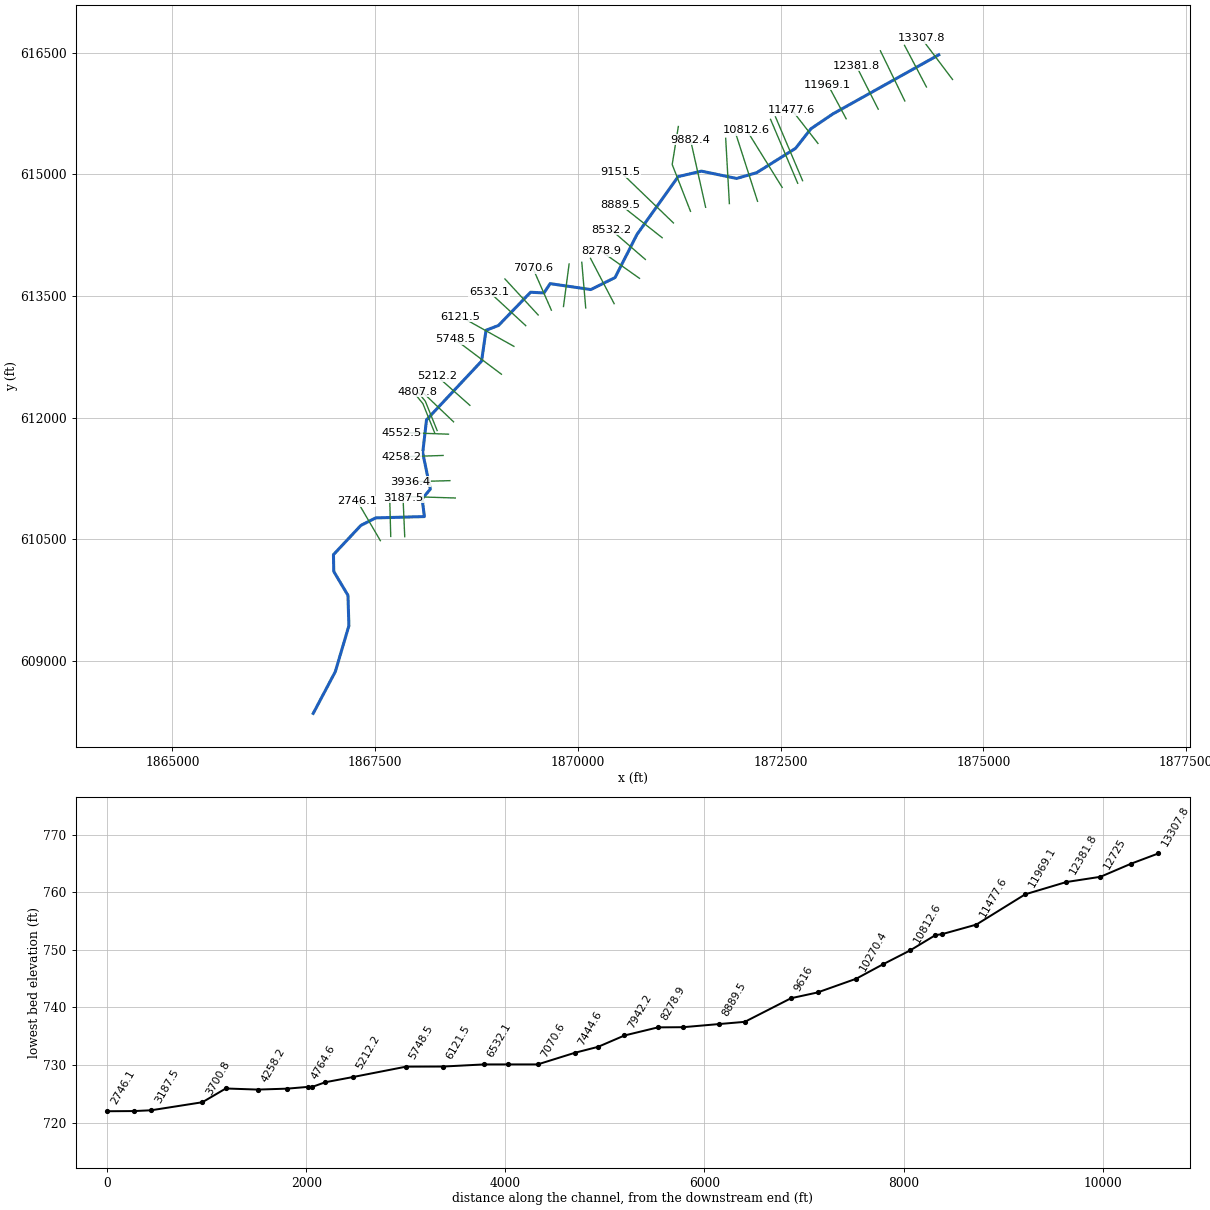
--- RushCreek.prj (project) ---

Proj Title=RushCreek
Current Plan=p01
Default Exp/Contr=0,0
English Units
Geom File=g01
Flow File=f01
Plan File=p01
BEGIN DESCRIPTION:
AMEC Environment & Infrastructure, 2013
Projection: NAD 1983 State Plane West Virginia South FIPS 4702 (US Feet)
Vertical Datum: NAVD 1988
END DESCRIPTION:
DSS Export Rating Curves= 0
DSS Export Rating Curve Sorted= 0
DSS Export Volume Flow Curves= 0
DXF OffsetX= 0
DXF OffsetY= 0
DXF ScaleX= 0
DXF ScaleY= 0

--- RushCreek.p01 (plan) ---

Plan Title=Floodplain
Program Version=4.00
Geom File=g01
Flow File=f01
K Sum by GR=0
Std Step Tol=0.01
Critical Tol=0.01
Num of Std Step Trials=20
Max Error Tol=0.3
Flow Tol Ratio=0.001
Split Flow NTrial=30
Split Flow Tol=0.02
Split Flow Ratio=0.02
Log Output Level=0
Friction Slope Method=1
Unsteady Friction Slope Method=2
Unsteady Bridges Friction Slope Method=1
Global Log Level=0
CheckData=False
Run HTab=0
Run UNet=0
Run PostProcess=0
UNET Theta=0
UNET Theta Warmup=0
UNET ZTol=0
UNET ZSATol=0
UNET MxIter=0
UNET MaxInSteps=0
UNET DtIC=0
UNET DtMin=0
UNET MaxCRTS=0
UNET WFStab=0
UNET SFStab=0
UNET WFX=0
UNET SFX=0
UNET DSS MLevel=0
UNET DZMax Abort=0
UNET Convert EG Bridges=0
UNET Use Existing IB Tables=0
UNET Froude Limit=0
UNET Froude Power=0
Write IC File=0
Echo Input=False
Echo Output=False
Write Detailed=0

--- RushCreek.f01 (steady flow) ---

Flow Title=NFF Regression Equation
Program Version=4.10
Number of Profiles= 1
Profile Names=P100yr
River Rch & RM=RushCreek,Main            ,13307.8
 999.236
River Rch & RM=RushCreek,Main            ,11477.6
1038.482
River Rch & RM=RushCreek,Main            ,9151.5
1152.183
River Rch & RM=RushCreek,Main            ,8889.5
 1831.97
River Rch & RM=RushCreek,Main            ,7942.2
1840.403
River Rch & RM=RushCreek,Main            ,414.4
2043.571
River Rch & RM=RushCreek,Main            ,281.9
2045.573
Boundary for River Rch & Prof#=RushCreek,Main            , 1
Up Type= 0
Dn Type= 3
Dn Slope=0.005
DSS Import GetInterval= 0
DSS Import GetPeak= 0
DSS Import FillOption= 0

--- RushCreek.g01 (geometry) ---

Geom Title=USGS 3m DEM
Program Version=4.10

River Reach=RushCreek       ,Main
Reach XY= 30
     1874451.365      616473.391     1873147.113       615745.65
     1872874.454      615561.546     1872685.161      615320.134
     1872204.899      615019.367     1871957.488      614948.445
     1871523.303      615038.737     1871236.746      614970.993
     1870729.651      614258.915     1870458.661       613726.44
     1870160.034      613578.096     1869658.118      613651.018
     1869581.707      613536.391     1869416.718      613545.067
     1869020.762      613135.184     1868867.522      613076.328
      1868812.38      612695.765     1868133.345      611971.544
     1868086.471      611565.149     1868180.272      611117.079
     1868079.547      610997.241     1868107.085      610778.447
     1867506.743       610762.08     1867324.391      610670.026
     1866985.746      610308.774     1866989.395      610101.646
     1867164.649       609806.87     1867176.095      609431.876
     1867008.383      608865.562     1866736.218      608351.389

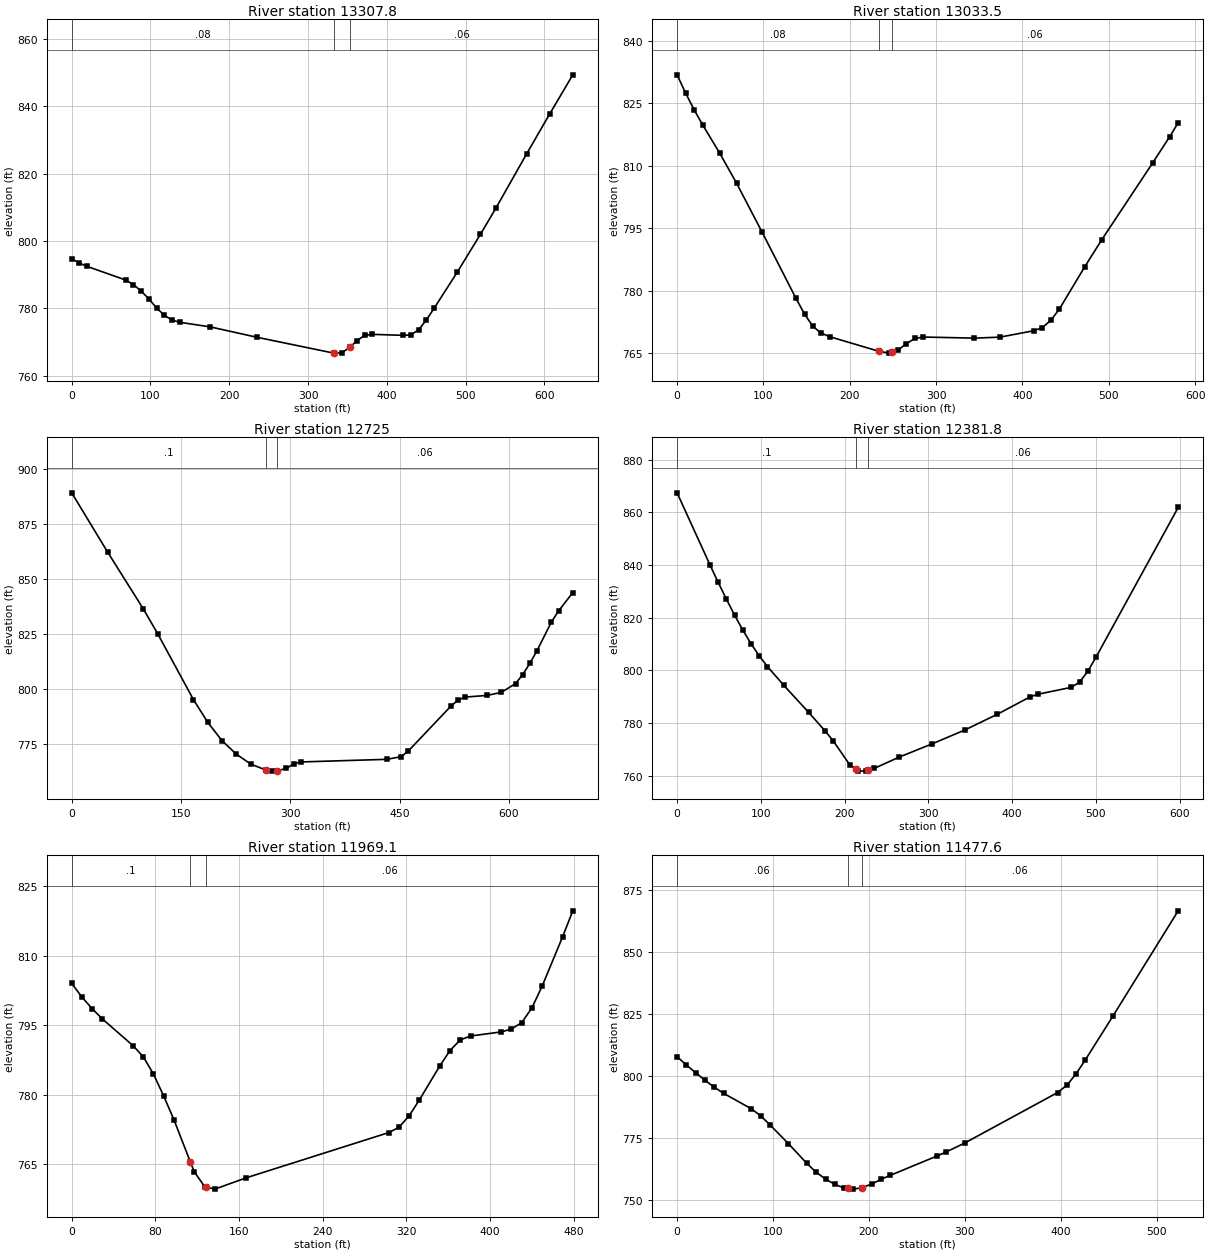
Type RM Length L Ch R = 1 ,13307.8 ,277.9,274.3,270.6
XS GIS Cut Line= 2
     1874620.951      616168.816     1874237.412      616676.441
#Sta/Elev= 30
       0  794.72     9.8  793.45    19.6  792.46    68.5  788.42    78.3  787.08
    88.1  785.17    97.9  782.82   107.7  780.15   117.5  777.96   127.2  776.57
     137  775.89   176.2   774.5   234.9  771.45   332.8  766.73   342.6  766.82
   353.1  768.41   362.2  770.47     372  771.98   381.7   772.3   420.9  772.01
   430.7  772.14   440.5  773.68   450.2  776.56     460  779.99   489.4  790.72
   518.8  801.94   538.4  809.69   577.5  825.82   606.9  837.72   636.2  849.31
#Mann= 3 , 0 , 0
       0     .08       0   332.8    .045       0   353.1     .06       0
Bank Sta=332.8,353.1
XS Rating Curve= 0 ,0
Exp/Cntr=0.3,0.1

Type RM Length L Ch R = 1 ,13033.5 ,309.2,308.5,307.8
XS GIS Cut Line= 2
     1874298.783      616076.433      1874028.47      616590.029
#Sta/Elev= 30
       0  831.89     9.8  827.53    19.7  823.49    29.5  819.89    49.2  813.11
    68.9  805.82    98.4  794.08   137.7  778.12   147.6  774.34   157.4  771.36
   167.2  769.73   177.1  768.88   234.1  765.37   245.9  764.95   249.1  765.18
   255.8  765.65   265.6  767.24   275.4  768.47   285.3  768.82   344.3  768.56
   373.8  768.79   413.2  770.34     423   771.1   432.8  772.81   442.7  775.52
   472.2  785.72   491.8  792.19   550.9  810.72   570.6  817.01   580.4  820.36
#Mann= 3 , 0 , 0
       0     .08       0   234.1    .045       0   249.1     .06       0
Bank Sta=234.1,249.1
XS Rating Curve= 0 ,0
Exp/Cntr=0.3,0.1

Type RM Length L Ch R = 1 ,12725   ,342.8,343.2,343.5
XS GIS Cut Line= 2
     1874031.849      615904.108     1873731.125       616522.45
#Sta/Elev= 30
       0  889.21    49.1  862.36    98.2  836.46   117.9  825.17     167  795.21
   186.6  784.88   206.3   776.5   225.9  770.38   245.6  765.89   266.4  763.17
     275  762.67   281.4  762.75   294.7  763.96   304.5  765.91   314.3  766.84
   432.2  768.03   451.8  769.22   461.7  771.75   520.6  792.32   530.4  795.01
   540.2  796.34   569.7  797.09   589.4  798.45     609  802.47   618.8  806.55
   628.7  811.67   638.5  817.45   658.1  830.38     668  835.48   687.6  843.86
#Mann= 3 , 0 , 0
       0      .1       0   266.4    .045       0   281.4     .06       0
Bank Sta=266.4,281.4
XS Rating Curve= 0 ,0
Exp/Cntr=0.3,0.1

Type RM Length L Ch R = 1 ,12381.8 ,412.1,412.7,413.2
XS GIS Cut Line= 2
     1873704.093       615802.74      1873433.78       616336.61
#Sta/Elev= 30
       0  867.41    39.2   840.1      49  833.46    58.9  827.04    68.7  820.95
    78.5   815.3    88.3  810.11    98.1  805.55   107.9  801.45   127.5  794.31
     157  784.11   176.6  777.06   186.4  773.28     206  764.26   213.2  762.48
   215.8  761.84   225.6  761.76   228.2  762.03   235.4  762.79   264.9  767.04
   304.1  772.05   343.4  777.34   382.6  783.37   421.8     790   431.6     791
   470.9  793.57   480.7  795.57   490.5  799.66   500.3  805.03   598.4  861.84
#Mann= 3 , 0 , 0
       0      .1       0   213.2    .045       0   228.2     .06       0
Bank Sta=213.2,228.2
XS Rating Curve= 0 ,0
Exp/Cntr=0.3,0.1

Type RM Length L Ch R = 1 ,11969.1 ,487.1,491.4,495.8
XS GIS Cut Line= 2
      1873308.76      615684.478     1873082.372      616106.843
#Sta/Elev= 30
       0  803.99     9.8  801.05    19.6  798.53    29.3  796.35    58.7  790.56
    68.5  788.17    78.2  784.43      88   779.7    97.8  774.57   113.4  765.52
   117.4   763.3   127.1  760.18   128.4  760.11   136.9  759.63   166.3  762.03
   303.2  771.83     313  772.97   322.7  775.46   332.5  778.87   352.1  786.25
   361.8  789.53   371.6  791.82   381.4  792.66   410.8  793.54   420.5  794.17
   430.3  795.53   440.1  798.73   449.9  803.43   469.4  814.03   479.2  819.66
#Mann= 3 , 0 , 0
       0      .1       0   113.4    .045       0   128.4     .06       0
Bank Sta=113.4,128.4
XS Rating Curve= 0 ,0
Exp/Cntr=0.3,0.1

Type RM Length L Ch R = 1 ,11477.6 ,348.5,342.7,336.7
XS GIS Cut Line= 2
     1872960.731      615380.376     1872639.734      615792.604
#Sta/Elev= 30
       0  807.77     9.7  804.44    19.4   801.3      29  798.31    38.7  795.49
    48.4  793.03    77.4  786.77    87.1  783.96    96.8  780.32   116.1  772.71
   135.4  764.71   145.1  761.18   154.8  758.41   164.5  756.28   174.2  754.82
   177.7  754.66   183.8  754.37   192.7  754.93   203.2  756.47   212.9  758.36
   222.5  759.96   270.9  767.71   280.6  769.36   299.9  772.96   396.7  793.31
   406.4  796.25     416  800.85   425.7   806.5   454.7  824.31   522.5  866.62
#Mann= 3 , 0 , 0
       0     .06       0   177.7    .045       0   192.7     .06       0
Bank Sta=177.7,192.7
XS Rating Curve= 0 ,0
Exp/Cntr=0.3,0.1

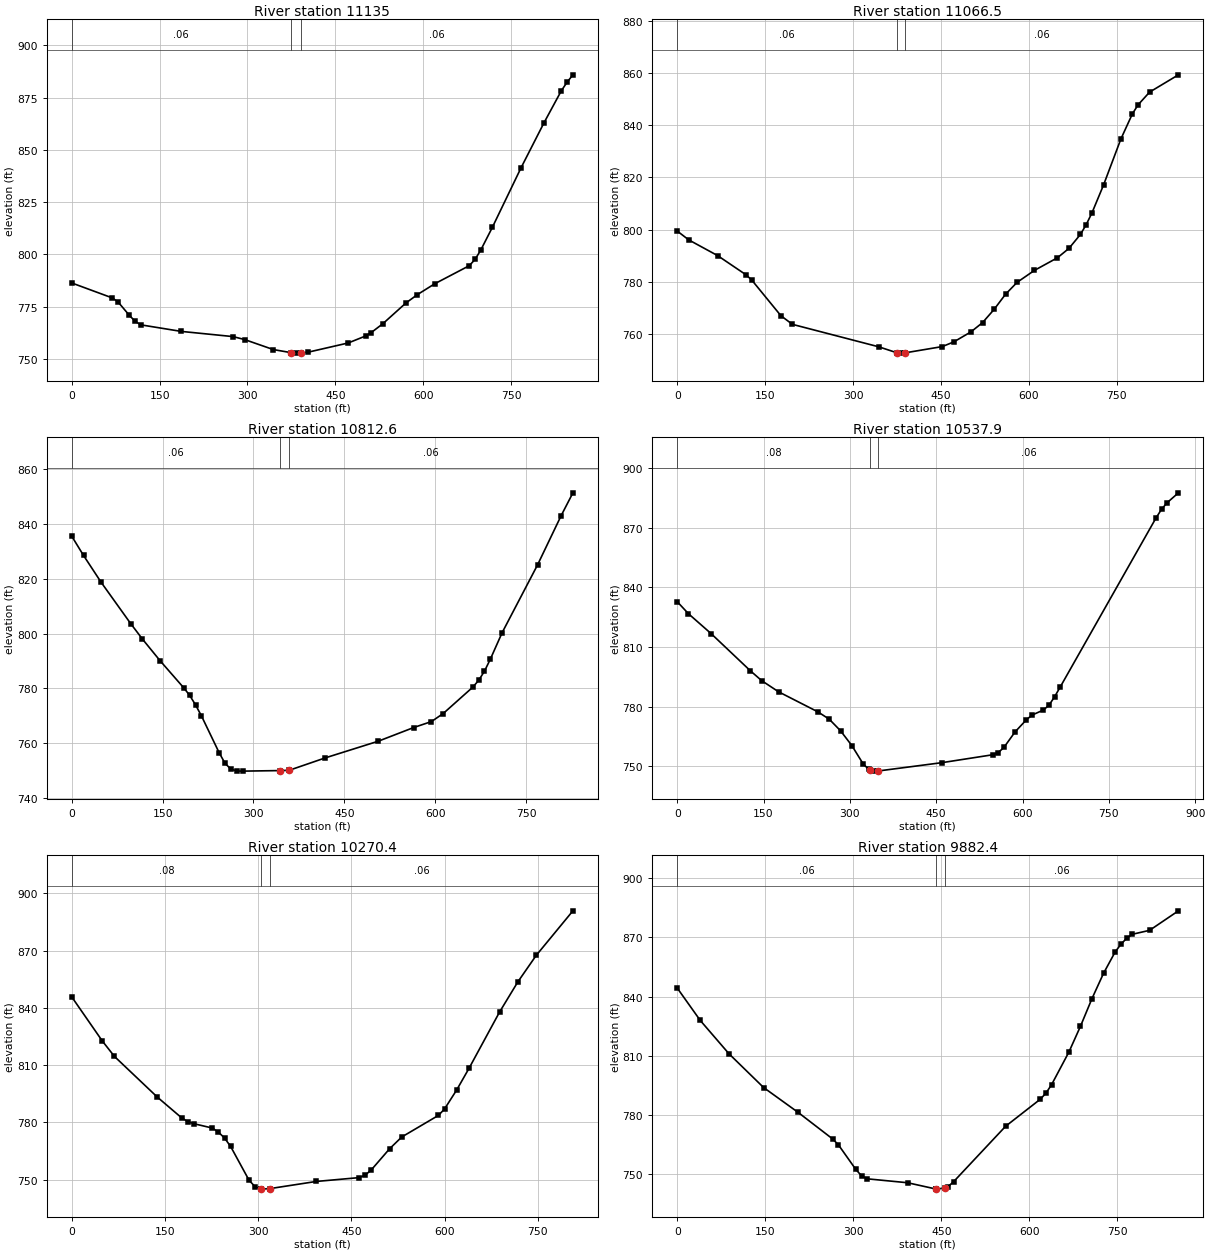
Type RM Length L Ch R = 1 ,11135   ,68.5,68.5,68.5
XS GIS Cut Line= 2
     1872771.512      614920.842     1872436.999      615708.131
#Sta/Elev= 30
       0  786.29    68.8  779.18    78.7  777.33    98.3  770.81   108.2  767.94
     118  766.25   186.8  763.12   275.3  760.63     295  759.22   344.1  754.42
   373.6  752.99   383.5  752.72     392  752.78   403.1  753.15     472  757.59
   501.4   760.9   511.3  762.58   530.9  766.76   570.3  776.69   589.9   780.7
   619.4  785.88   678.4  794.54   688.3  797.52   698.1  802.01   717.8  812.84
   766.9  841.41   806.2     863   835.7  878.29   845.6   882.4   855.4  885.87
#Mann= 3 , 0 , 0
       0     .06       0   373.6    .045       0     392     .06       0
Bank Sta=373.6,392
XS Rating Curve= 0 ,0
Exp/Cntr=0.3,0.1

Type RM Length L Ch R = 1 ,11066.5 ,249.1,253.9,256
XS GIS Cut Line= 2
     1872710.937       614889.41     1872376.424      615676.698
#Sta/Elev= 30
       0  799.42    19.7  796.02    68.8  790.01     118  782.53   127.8  780.44
     177   766.9   196.6  763.59   344.1  754.96   374.5  752.71   383.5  752.54
   389.5  752.67   452.3  755.05     472  756.84   501.4  760.71   521.1  764.25
   540.8  769.32   560.4  775.16   580.1  779.72   609.6   784.3   648.9  789.15
   668.6  792.76   688.3  798.15   698.1  801.91   707.9  806.41   727.6  817.08
   757.1   834.7   776.8  844.39   786.6  847.89   806.2  852.76   855.4   859.4
#Mann= 3 , 0 , 0
       0     .06       0   374.5    .045       0   389.5     .06       0
Bank Sta=374.5,389.5
XS Rating Curve= 0 ,0
Exp/Cntr=0.3,0.1

Type RM Length L Ch R = 1 ,10812.6 ,280.4,274.8,269.1
XS GIS Cut Line= 2
     1872519.554      614838.334     1872083.356      615541.459
#Sta/Elev= 30
       0  835.49    19.5  828.46    48.7  818.64    97.4  803.62   116.8  797.98
     146  790.08     185  780.22   194.7   777.5   204.4  774.02   214.2  769.99
   243.4  756.59   253.1  752.72   262.8  750.62   272.6  749.93   282.3  749.89
   343.8  750.09   358.8  750.18   418.6  754.72   506.2   760.8   564.6  765.78
   593.8  767.94   613.3  770.88     662  780.46   671.7  782.93   681.4   786.3
   691.2  790.74   710.6  800.36     769  825.02     808  842.98   827.4  851.28
#Mann= 3 , 0 , 0
       0     .06       0   343.8    .045       0   358.8     .06       0
Bank Sta=343.8,358.8
XS Rating Curve= 0 ,0
Exp/Cntr=0.3,0.1

Type RM Length L Ch R = 1 ,10537.9 ,273.1,267.5,261.7
XS GIS Cut Line= 2
     1872215.734      614666.893     1871948.807      615495.886
#Sta/Elev= 30
       0  832.78    19.6   826.7    58.7  816.76   127.2  797.96   146.8  793.02
   176.1  787.41   244.6  777.28   264.2   773.6   283.8  767.78   303.4  760.35
   322.9   751.2   332.7  748.33   334.4  748.18   342.5  747.46   349.4  747.54
   459.9  751.72     548  755.69   557.8  756.78   567.6  759.36   587.1  767.22
   606.7  773.31   616.5  775.67   636.1  778.21   645.8  780.57   655.6  784.82
   665.4  789.76   831.8  874.85   841.6  879.32   851.3  882.62   870.9   887.6
#Mann= 3 , 0 , 0
       0     .08       0   334.4    .045       0   349.4     .06       0
Bank Sta=334.4,349.4
XS Rating Curve= 0 ,0
Exp/Cntr=0.3,0.1

Type RM Length L Ch R = 1 ,10270.4 ,384.3,388,391.6
XS GIS Cut Line= 2
     1871868.512      614638.681     1871822.939      615443.803
#Sta/Elev= 30
       0  845.75    49.2  822.63    68.8  814.51   137.7  793.22     177   782.3
   186.8  780.36   196.7  779.25   226.2  776.99     236  774.87   245.9  771.75
   255.7  767.32   285.2  749.69     295  746.22   304.6  745.01   304.9  744.97
   319.6  745.28   393.4  748.99   462.2     751     472  752.26   481.9  755.02
   511.4  766.11     531   772.3   590.1  783.64   599.9     787   619.6  797.07
   639.2  808.28   688.4  837.82   717.9  853.67   747.4  867.52   806.4  890.86
#Mann= 3 , 0 , 0
       0     .08       0   304.6    .045       0   319.6     .06       0
Bank Sta=304.6,319.6
XS Rating Curve= 0 ,0
Exp/Cntr=0.3,0.1

Type RM Length L Ch R = 1 ,9882.4  ,263.7,266.3,269.3
XS GIS Cut Line= 2
     1871575.543      614593.108     1871388.911      615426.442
#Sta/Elev= 30
       0  844.35    39.3  827.93    88.3  811.05   147.2     794   206.1   781.4
     265  767.94   274.8  764.95   304.3  752.56   314.1   749.3   323.9   747.8
   392.6  745.82   441.4  742.61   441.7  742.59   456.4  743.21   461.3  743.82
   471.2  746.43   559.5  774.38   618.4  788.02   628.2  791.11     638   795.5
   667.5  812.01   687.1  824.98   706.7  838.98   726.4  851.77     746  862.49
   755.8  866.42   765.6  869.45   775.4  871.54   804.9  873.54     854  883.41
#Mann= 3 , 0 , 0
       0     .06       0   441.4    .045       0   456.4     .06       0
Bank Sta=441.4,456.4
XS Rating Curve= 0 ,0
Exp/Cntr=0.3,0.1

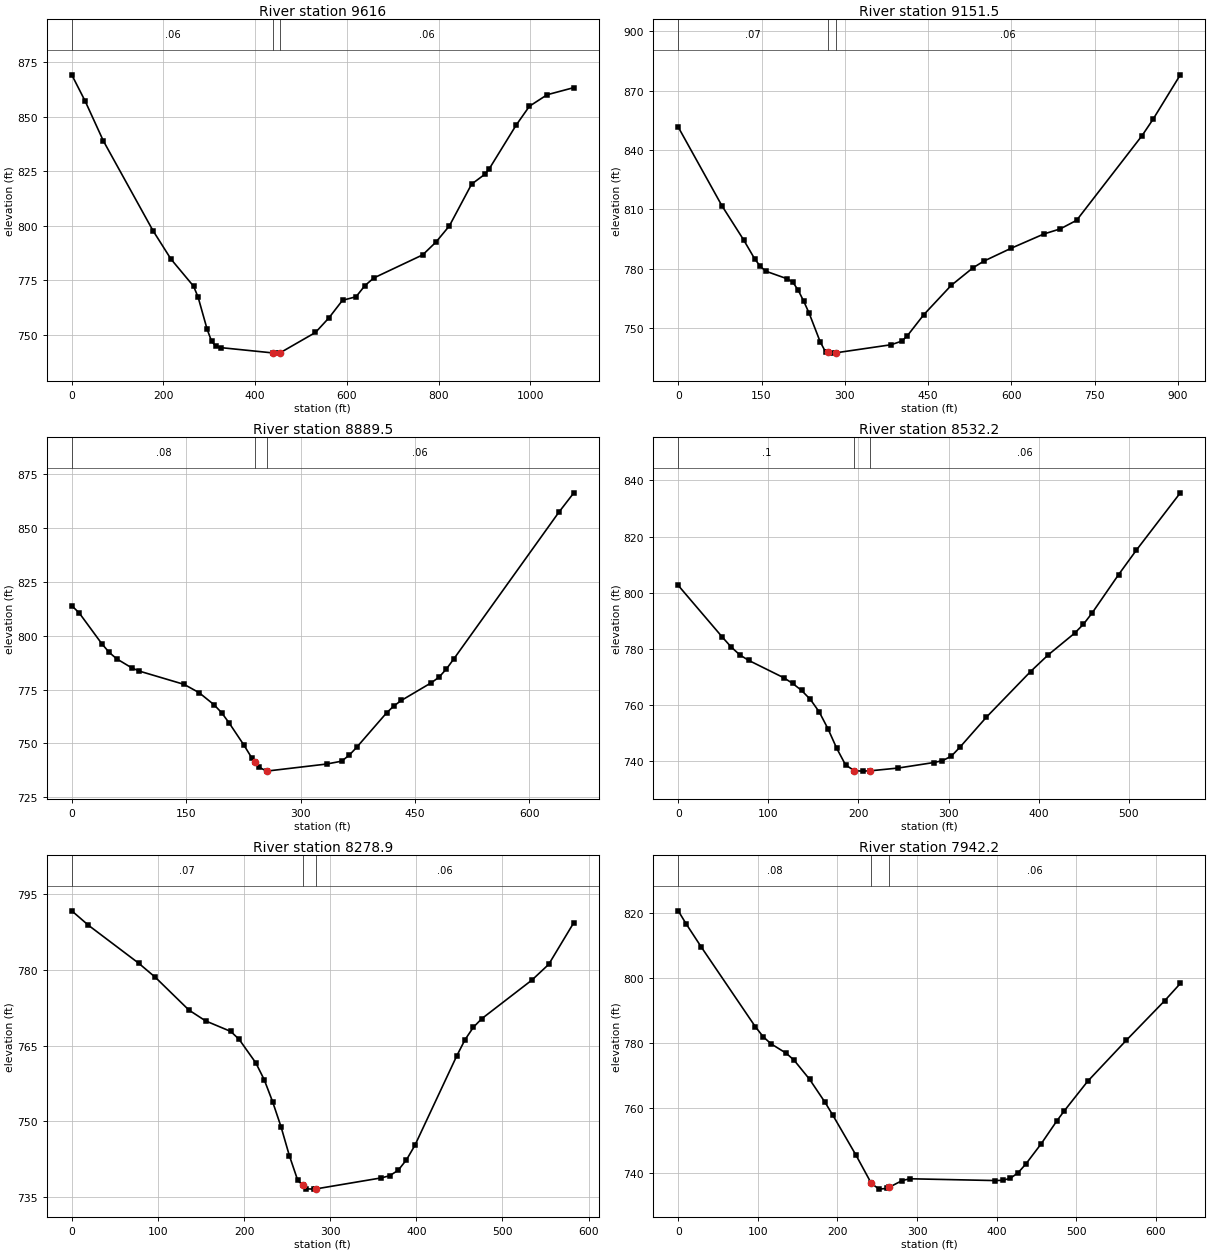
Type RM Length L Ch R = 1 ,9616    ,453.5,464.5,474.9
XS GIS Cut Line= 3
     1871388.911      614543.195     1871163.217      615120.452
     1871239.172      615589.202
#Sta/Elev= 30
       0  869.34    29.5  857.14    68.9     839   177.1   797.8   216.4  784.72
   265.6   772.3   275.5  767.24   295.2  752.49     305  746.97   314.8  744.65
   324.7  744.12   439.4  741.66   442.7  741.59   454.4  741.76   531.3  751.07
   560.8   757.8   590.3  765.84   619.8  767.46   639.2   772.6   658.6   776.1
   765.2   786.7   794.2  792.59   823.3  799.99   871.8  819.17   900.8  823.71
   910.5  826.28   968.7  846.18   997.8  854.92  1036.5   860.2  1094.7  863.47
#Mann= 3 , 0 , 0
       0     .06       0   439.4    .045       0   454.4     .06       0
Bank Sta=439.4,454.4
XS Rating Curve= 0 ,0
Exp/Cntr=0.3,0.1

Type RM Length L Ch R = 1 ,9151.5  ,260.4,262,263.6
XS GIS Cut Line= 2
     1871178.408      614399.966     1870527.366      615027.136
#Sta/Elev= 30
       0   851.6    78.6  811.91   117.9  794.59   137.6  785.09   147.4  781.44
   157.2   778.9   196.5  774.98   206.4   773.3   216.2  769.15     226  763.66
   235.8  757.57   255.5  743.26   265.3  738.06   268.8  737.86   275.1  737.49
   283.8  737.65   383.2  741.72   402.9  743.59   412.7  746.33   442.2  756.92
   491.3  771.64   530.6  780.55   550.2  783.92   599.4  790.43   658.3  797.63
   687.8   800.2   717.3  804.54   835.2  847.32   854.9  855.53     904  877.98
#Mann= 3 , 0 , 0
       0     .07       0   268.8    .045       0   283.8     .06       0
Bank Sta=268.8,283.8
XS Rating Curve= 0 ,0
Exp/Cntr=0.3,0.1

Type RM Length L Ch R = 1 ,8889.5  ,358.1,357.3,355.7
XS GIS Cut Line= 2
     1871039.519      614217.674     1870523.026       614625.66
#Sta/Elev= 30
       0  813.94     9.8  810.56    39.3  796.31    49.1  792.24    58.9  789.27
    78.6  785.08    88.4  783.58   147.4  777.38     167  773.52   186.6  767.91
   196.5  764.22   206.3  759.48     226  749.02   235.8  743.34   240.3  741.32
   245.6  738.94   255.3   737.1     334  740.39   353.7  741.72   363.5  744.43
   373.3  748.08   412.6  764.12   422.4  767.43   432.2  769.96   471.5  778.19
   481.4  780.73   491.2  784.58     501   789.3   638.6  857.39   658.2  866.38
#Mann= 3 , 0 , 0
       0     .08       0   240.3    .045       0   255.3     .06       0
Bank Sta=240.3,255.3
XS Rating Curve= 0 ,0
Exp/Cntr=0.3,0.1

Type RM Length L Ch R = 1 ,8532.2  ,250.9,253.3,256.2
XS GIS Cut Line= 2
     1870832.101      613949.535     1870411.278      614314.535
#Sta/Elev= 30
       0  802.64    48.9  784.25    58.6  780.77    68.4  777.89    78.2  775.96
   117.3  769.75     127  767.75   136.8  765.28   146.6  762.08   156.4  757.64
   166.1  751.66   175.9  744.65   185.7  738.75   195.5  736.69   205.2  736.56
   213.1  736.67   244.3  737.67   283.4  739.61   293.2  740.27     303  741.88
   312.7  745.12     342  755.78   390.9  771.98   410.5  777.92   439.8  785.63
   449.6  788.82   459.3  792.85   488.6  806.47   508.2  815.13   557.1  835.58
#Mann= 3 , 0 , 0
       0      .1       0   195.5    .045       0   213.1     .06       0
Bank Sta=195.5,213.1
XS Rating Curve= 0 ,0
Exp/Cntr=0.3,0.1

Type RM Length L Ch R = 1 ,8278.9  ,347.2,336.7,325.9
XS GIS Cut Line= 2
     1870760.005      613716.372     1870284.311      614053.178
#Sta/Elev= 30
       0  791.72    19.4  788.85    77.7  781.33    97.1  778.52     136  772.04
   155.4  769.89   184.6   767.8   194.3  766.23   213.7  761.56   223.4  758.24
   233.1   753.9   242.9  748.92   252.6  743.18   262.3  738.29     268  737.29
     272  736.59   281.7  736.53     283  736.56   359.4  738.76   369.1  739.19
   378.9  740.26   388.6  742.35   398.3  745.19   446.9  762.93   456.6  766.18
   466.3  768.64     476  770.33   534.3     778   553.7   781.1   582.9  789.39
#Mann= 3 , 0 , 0
       0     .07       0     268    .045       0     283     .06       0
Bank Sta=268,283
XS Rating Curve= 0 ,0
Exp/Cntr=0.3,0.1

Type RM Length L Ch R = 1 ,7942.2  ,274,265,256.1
XS GIS Cut Line= 2
     1870447.505      613403.872     1870155.838        613962.9
#Sta/Elev= 30
       0  820.53     9.7  816.62    29.1  809.36      97   784.9   106.7  781.89
   116.4  779.74   135.8  776.79   145.5  774.68   164.9  768.84   184.3  761.78
     194  757.87   223.1   745.6   242.5  736.88   252.2  735.12   261.9  735.34
   265.2  735.73   281.3  737.76     291   738.3   397.7  737.75   407.4  737.82
   417.1  738.45   426.8  740.15   436.5  742.82   455.9  749.07   475.3  756.01
     485  759.21   514.1   768.2   562.6  780.78   611.1     793   630.5  798.23
#Mann= 3 , 0 , 0
       0     .08       0   242.5    .045       0   265.2     .06       0
Bank Sta=242.5,265.2
XS Rating Curve= 0 ,0
Exp/Cntr=0.3,0.1

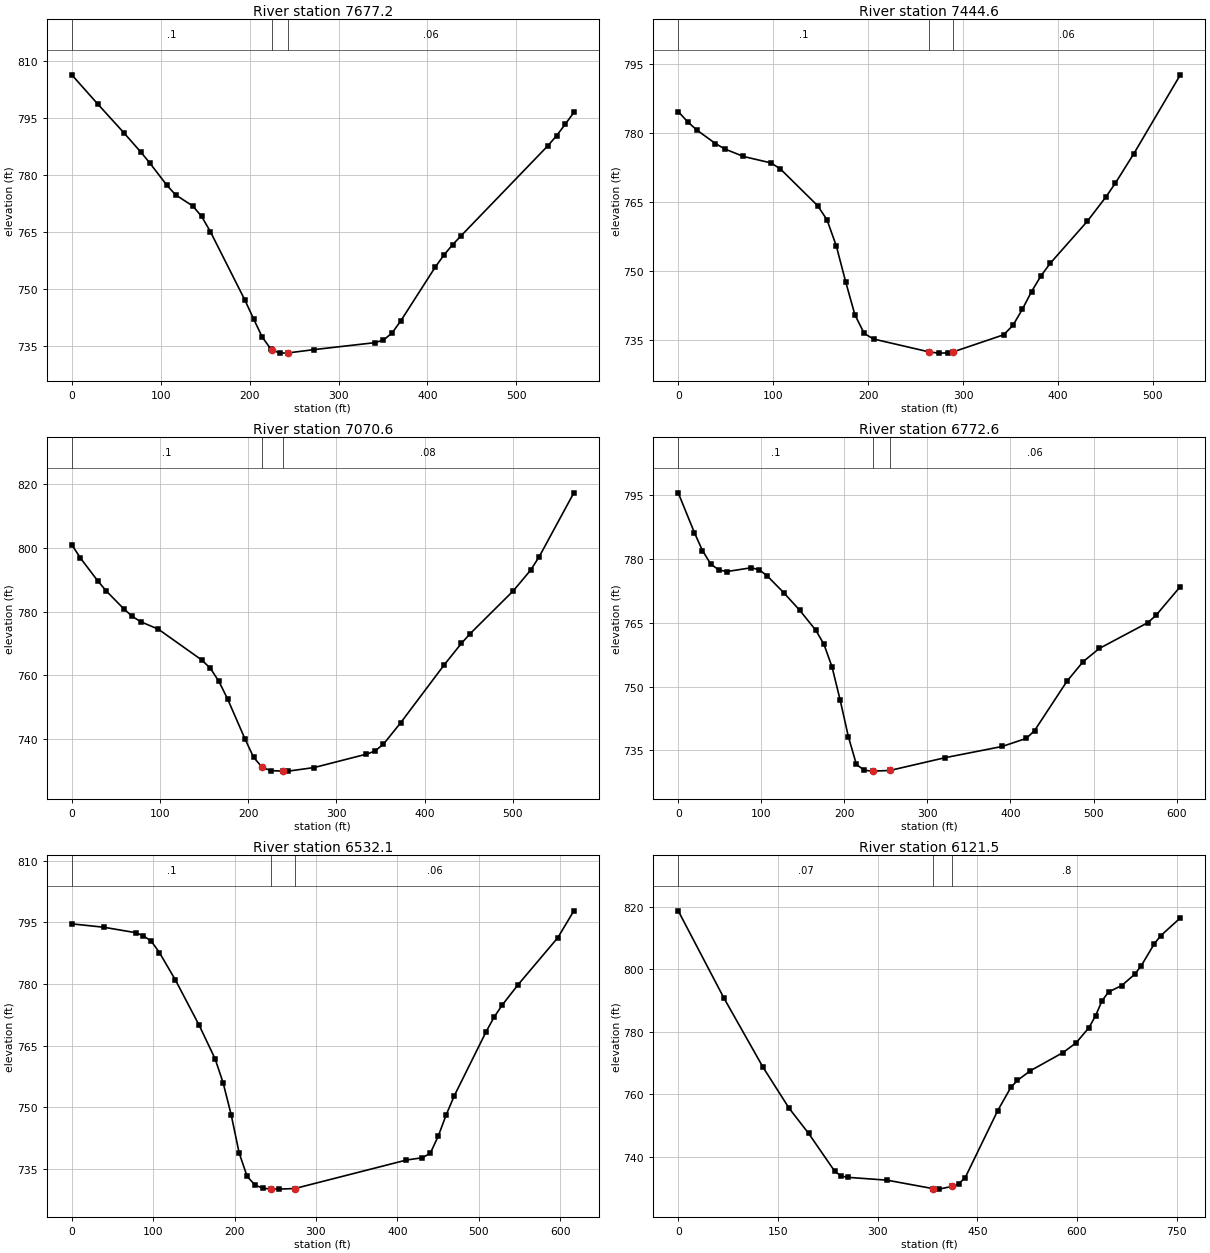
Type RM Length L Ch R = 1 ,7677.2  ,237,232.6,227.6
XS GIS Cut Line= 2
     1870096.811      613351.789       1870048.2      613914.289
#Sta/Elev= 30
       0  806.41    29.2  798.73    58.4   791.2    77.9  786.01    87.6  783.24
   107.1   777.3   116.8  774.81   136.3  771.84     146  769.14   155.8  765.16
   194.7  747.11   204.4   742.2   214.2  737.37   223.9  734.21   224.9   734.1
   233.6  733.15   243.4  733.21   272.6  734.08   340.7   735.9   350.4  736.57
   360.2  738.45   369.9  741.61   408.8  755.82   418.6     759   428.3  761.69
     438  764.09   535.4  787.74   545.1  790.35   554.9  793.39   564.6  796.51
#Mann= 3 , 0 , 0
       0      .1       0   224.9    .045       0   243.4     .06       0
Bank Sta=224.9,243.4
XS Rating Curve= 0 ,0
Exp/Cntr=0.3,0.1

Type RM Length L Ch R = 1 ,7444.6  ,361.1,374.1,386.2
XS GIS Cut Line= 2
     1869822.505       613369.15      1869891.95      613893.455
#Sta/Elev= 30
       0  784.69     9.8  782.48    19.6  780.66    39.2  777.73      49  776.55
    68.6  774.92    97.9   773.5   107.7  772.18   146.9  764.19   156.7  761.13
   166.5  755.46   176.3   747.7   186.1  740.46   195.9  736.41   205.7  735.19
   264.4  732.38   274.2  732.12     284  732.16   289.8   732.4   342.8  736.11
   352.6  738.16   362.4  741.63   372.2  745.52     382  748.89   391.8  751.65
   430.9   760.8   450.5   766.1   460.3  769.05   479.9  775.51   528.9  792.68
#Mann= 3 , 0 , 0
       0      .1       0   264.4    .045       0   289.8     .06       0
Bank Sta=264.4,289.8
XS Rating Curve= 0 ,0
Exp/Cntr=0.3,0.1

Type RM Length L Ch R = 1 ,7070.6  ,290.3,298,305.5
XS GIS Cut Line= 2
       1869673.2      613324.011     1869444.033      613844.844
#Sta/Elev= 30
       0   800.9     9.8  796.71    29.4  789.59    39.2  786.38    58.9  780.85
    68.7  778.44    78.5  776.76    98.1  774.47   147.2  764.86     157  762.27
   166.8  758.13   176.6  752.65   196.2  740.23     206  734.46   215.8  731.26
   225.6  730.25   239.1  730.11   245.3   730.1   274.7  731.22   333.6  735.38
   343.4  736.34   353.2  738.52   372.8  745.24   421.9  763.26   441.5  770.01
   451.3  773.02   500.4  786.47     520  792.92   529.8  797.16     569   817.1
#Mann= 3 , 0 , 0
       0      .1       0   215.8    .045       0   239.1     .08       0
Bank Sta=215.8,239.1
XS Rating Curve= 0 ,0
Exp/Cntr=0.3,0.1

Type RM Length L Ch R = 1 ,6772.6  ,238.2,240.5,242.8
XS GIS Cut Line= 2
     1869510.005      613264.983     1869100.283      613709.428
#Sta/Elev= 30
       0  795.57    19.5  786.18    29.2  781.98      39  778.85    48.8  777.42
    58.5  777.05    87.8  777.94    97.5  777.48   107.2  776.01   126.8  772.12
   146.2  767.96   165.8   763.2   175.5   759.9   185.2   754.6     195  746.77
   204.8  738.24   214.5  731.67   224.2  730.29     234   730.1   254.7  730.25
   321.7  733.28     390   735.9   419.2  737.81     429  739.63     468  751.24
   487.5  755.86     507  758.96   565.5  765.04   575.2  766.75   604.5  773.51
#Mann= 3 , 0 , 0
       0      .1       0     234    .045       0   254.7     .06       0
Bank Sta=234,254.7
XS Rating Curve= 0 ,0
Exp/Cntr=0.3,0.1

Type RM Length L Ch R = 1 ,6532.1  ,405.3,410.6,415.1
XS GIS Cut Line= 2
     1869357.227      613133.039     1868904.102      613551.442
#Sta/Elev= 30
       0  794.64    39.2  793.82    78.3   792.5    88.1  791.73    97.9  790.37
   107.7  787.64   127.3  780.99   156.6  769.93   176.2  761.74     186  755.93
   195.8  748.22   205.6  738.93   215.4   733.2   225.2  731.08     235  730.31
   244.7  730.13   254.5   730.1   274.1  730.25   411.2  737.18   430.8  737.74
   440.5  738.86   450.3  743.03   460.1  748.24   469.9   752.8   509.1  768.43
   518.8  771.93   528.6  774.83   548.2  779.82   597.2   791.3   616.8  797.81
#Mann= 3 , 0 , 0
       0      .1       0   244.7    .045       0   274.1     .06       0
Bank Sta=244.7,274.1
XS Rating Curve= 0 ,0
Exp/Cntr=0.3,0.1

Type RM Length L Ch R = 1 ,6121.5  ,376.2,373,369.6
XS GIS Cut Line= 2
     1869211.394       612877.83     1868551.672      613245.886
#Sta/Elev= 30
       0  818.73    68.7  790.85   127.5  768.73   166.8   755.6   196.2  747.54
   235.5  735.42   245.3   733.9   255.1   733.5     314   732.6   382.6  729.92
   392.4  729.73   412.1  730.61   421.9  731.43   431.7  733.38   480.7  754.85
   500.4  762.24   510.2  764.48   529.8  767.59   578.8  773.39   598.5  776.48
   618.1  781.41   627.9  785.19   637.7  789.99   647.5   792.8   667.2  794.82
   686.8  798.44   696.6  801.15   716.2  808.17     726  810.78   755.4  816.46
#Mann= 3 , 0 , 0
       0     .07       0   382.6    .045       0   412.1      .8       0
Bank Sta=382.6,412.1
XS Rating Curve= 0 ,0
Exp/Cntr=0.3,0.1

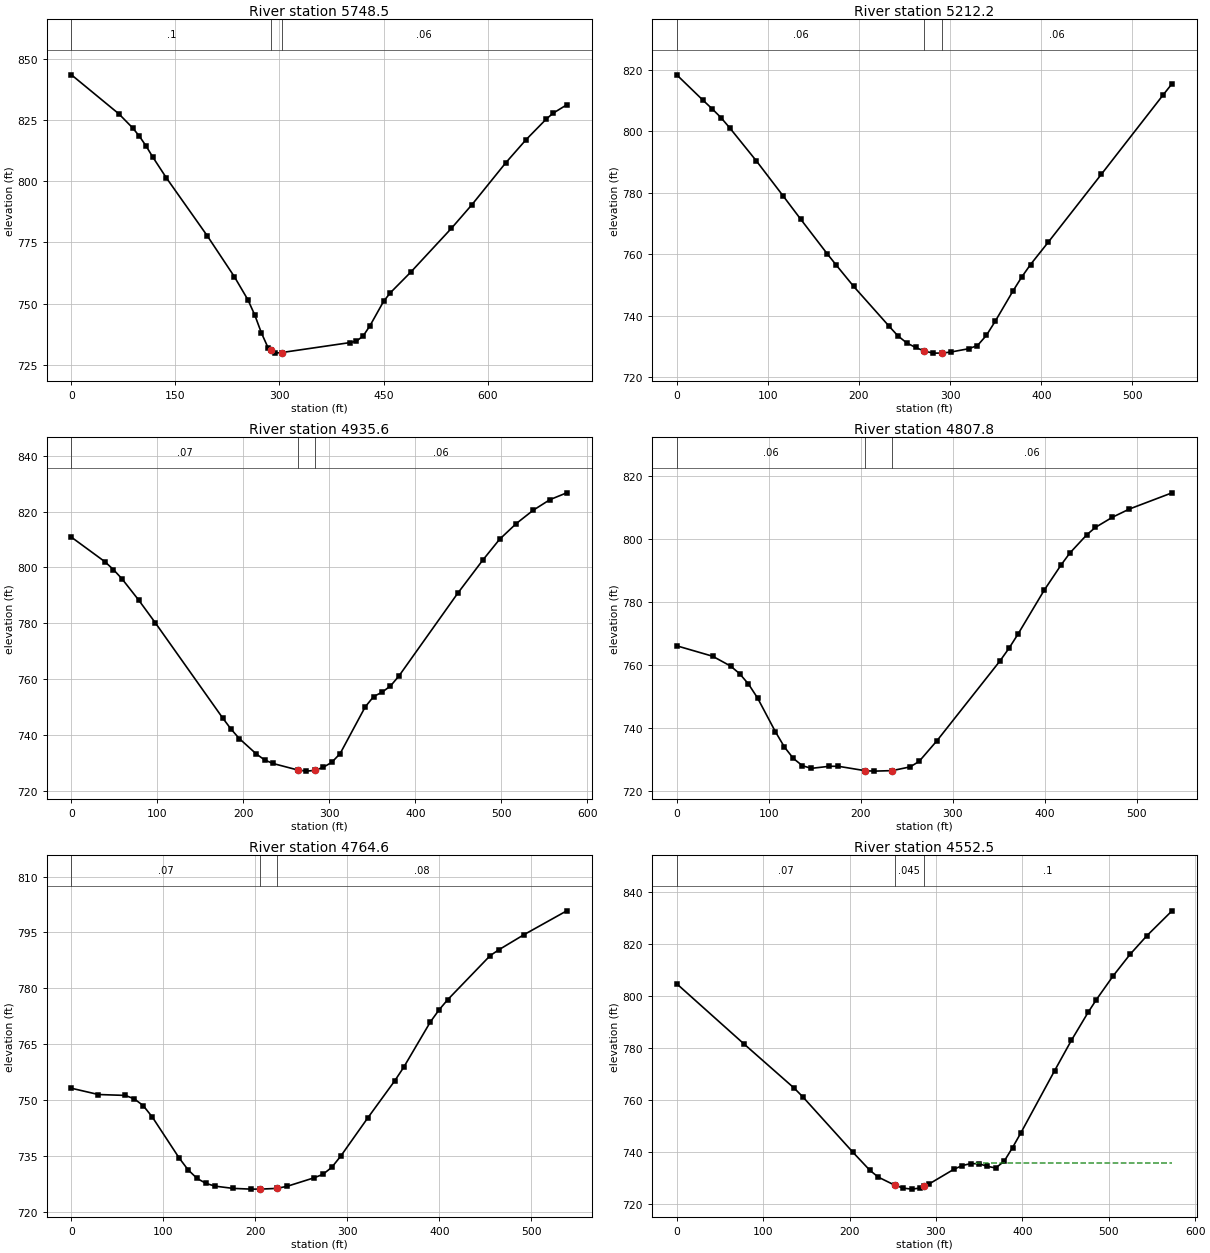
Type RM Length L Ch R = 1 ,5748.5  ,538.2,536.3,534.1
XS GIS Cut Line= 2
      1869056.88       612534.08       1868485.7        612962.9
#Sta/Elev= 30
       0  843.55    68.5  827.56    88.1  821.88    97.8  818.52   107.6  814.44
   117.4  809.87     137  801.36   195.7  777.77   234.8  761.04   254.4  751.56
   264.2  745.42     274  737.93   283.7  731.82   288.3  730.83   293.5  729.71
   303.3  729.95   401.2     734   410.9  734.58   420.7  736.74   430.5  740.93
   450.1  750.87   459.8  754.39   489.2  762.81   547.9  780.76   577.3  790.36
   626.2  807.54   655.5  817.01   684.9  825.52   694.7  827.88   714.2  831.28
#Mann= 3 , 0 , 0
       0      .1       0   288.3    .045       0   303.3     .06       0
Bank Sta=288.3,303.3
XS Rating Curve= 0 ,0
Exp/Cntr=0.3,0.1

Type RM Length L Ch R = 1 ,5212.2  ,277.4,276.6,275.8
XS GIS Cut Line= 2
     1868667.991        612150.4     1868261.741      612511.511
#Sta/Elev= 30
       0  818.38    29.1  810.04    38.8  807.35    48.5  804.48    58.2  801.12
    87.4  790.39   116.5  779.11   135.9  771.49     165  760.25   174.7  756.64
   194.1  749.61     233  736.66   242.6  733.54   252.4  731.21   262.1  729.75
   271.8  728.55   281.5   727.9   291.2  727.91   300.9  728.26   320.3  729.33
     330  730.36   339.7  733.64   349.4  738.21   368.8  748.02   378.5  752.61
   388.2   756.7   407.7  763.98   465.9  786.03   533.8  811.87   543.5  815.49
#Mann= 3 , 0 , 0
       0     .06       0   271.8    .045       0   291.2     .06       0
Bank Sta=271.8,291.2
XS Rating Curve= 0 ,0
Exp/Cntr=0.3,0.1

Type RM Length L Ch R = 1 ,4935.6  ,137.9,127.8,117.1
XS GIS Cut Line= 2
     1868466.602      611947.275     1868049.936      612344.844
#Sta/Elev= 30
       0   810.8      39     802    48.8   799.2    58.6  795.96    78.1  788.32
    97.6   780.1   175.7  746.11   185.5  742.08   195.2  738.66   214.8  733.19
   224.5  731.03   234.3  729.74   263.6  727.37   273.3     727   283.1  727.26
   292.8  728.38   302.6  730.13   312.4  733.27   341.6  750.02   351.4  753.72
   361.2  755.28   370.9  757.48   380.7  761.04     449  790.66   478.3   802.6
   497.8  810.05   517.3  815.71   536.9  820.46   556.4  824.26   575.9   826.7
#Mann= 3 , 0 , 0
       0     .07       0   263.6    .045       0   283.1     .06       0
Bank Sta=263.6,283.1
XS Rating Curve= 0 ,0
Exp/Cntr=0.3,0.1

Type RM Length L Ch R = 1 ,4807.8  ,45.7,43.1,43.4
XS GIS Cut Line= 3
     1868264.345      611839.636     1868118.512      612201.615
     1868024.762      612316.198
#Sta/Elev= 30
       0  766.03      39  762.72    58.5   759.6    68.3  757.19      78  753.87
    87.8  749.47   107.3   738.7   117.1  733.84   126.8  730.23   136.6  727.93
   146.3  727.09   165.9  727.75   175.6  727.75   204.9  726.34   214.6  726.21
   234.2  726.37   253.7  727.56   263.4  729.29   282.9   735.9   351.2  761.18
     361   765.2   370.7  769.66   399.5  783.76     418  791.84   427.3  795.53
   445.8  801.35     455  803.65   473.5  806.88     492   809.5   538.3  814.64
#Mann= 3 , 0 , 0
       0     .06       0   204.9    .045       0   234.2     .06       0
Bank Sta=204.9,234.2
XS Rating Curve= 0 ,0
Exp/Cntr=0.3,0.1

Type RM Length L Ch R = 1 ,4764.6  ,183.2,212.1,238.9
XS GIS Cut Line= 3
     1868234.479      611809.666     1868088.646      612171.645
     1867994.896      612286.228
#Sta/Elev= 30
       0  753.24    29.3  751.56    58.5  751.32    68.3   750.4      78  748.59
    87.8  745.56   117.1  734.54   126.8  731.37   136.6  729.06   146.3  727.73
   156.1     727   175.6   726.4   195.1   726.2   204.9   726.2   222.9  726.39
   234.2  726.94   263.4  729.21   273.2  730.15   282.9  732.03   292.7  735.05
     322  745.27   351.2  755.17     361  758.82   390.2  771.06   399.5  774.24
   408.8  776.95     455  788.77   464.3  790.33     492  794.43   538.3   800.8
#Mann= 3 , 0 , 0
       0     .07       0   204.9    .045       0   222.9     .08       0
Bank Sta=204.9,222.9
XS Rating Curve= 0 ,0
Exp/Cntr=0.3,0.1

Type RM Length L Ch R = 1 ,4552.5  ,292.9,294.3,295.6
XS GIS Cut Line= 2
     1868404.102      611794.497     1867831.186       611815.33
#Sta/Elev= 30
       0  804.63    77.7   781.6     136   764.6   145.8  761.32     204     740
   223.5  733.13   233.2  730.51   252.6  727.36   262.4  726.26   272.1  725.89
   281.8  726.31   286.1  726.95   291.5  727.75   320.7  733.48   330.4  734.92
   340.1  735.66   349.8  735.62   359.5  734.64   369.2     734     379  736.58
   388.7  741.82   398.4  747.51   437.3  771.25   456.7  782.88   476.1  793.63
   485.8  798.59   505.3  807.72   524.7   815.9   544.1  823.03   573.3   832.6
#Mann= 3 , 0 , 0
       0     .07       0   252.6    .045       0   286.1      .1       0
#XS Ineff= 2 , 0
                           346.5          735.92
Permanent Ineff=
       F       F
Bank Sta=252.6,286.1
XS Rating Curve= 0 ,0
Exp/Cntr=0.3,0.1

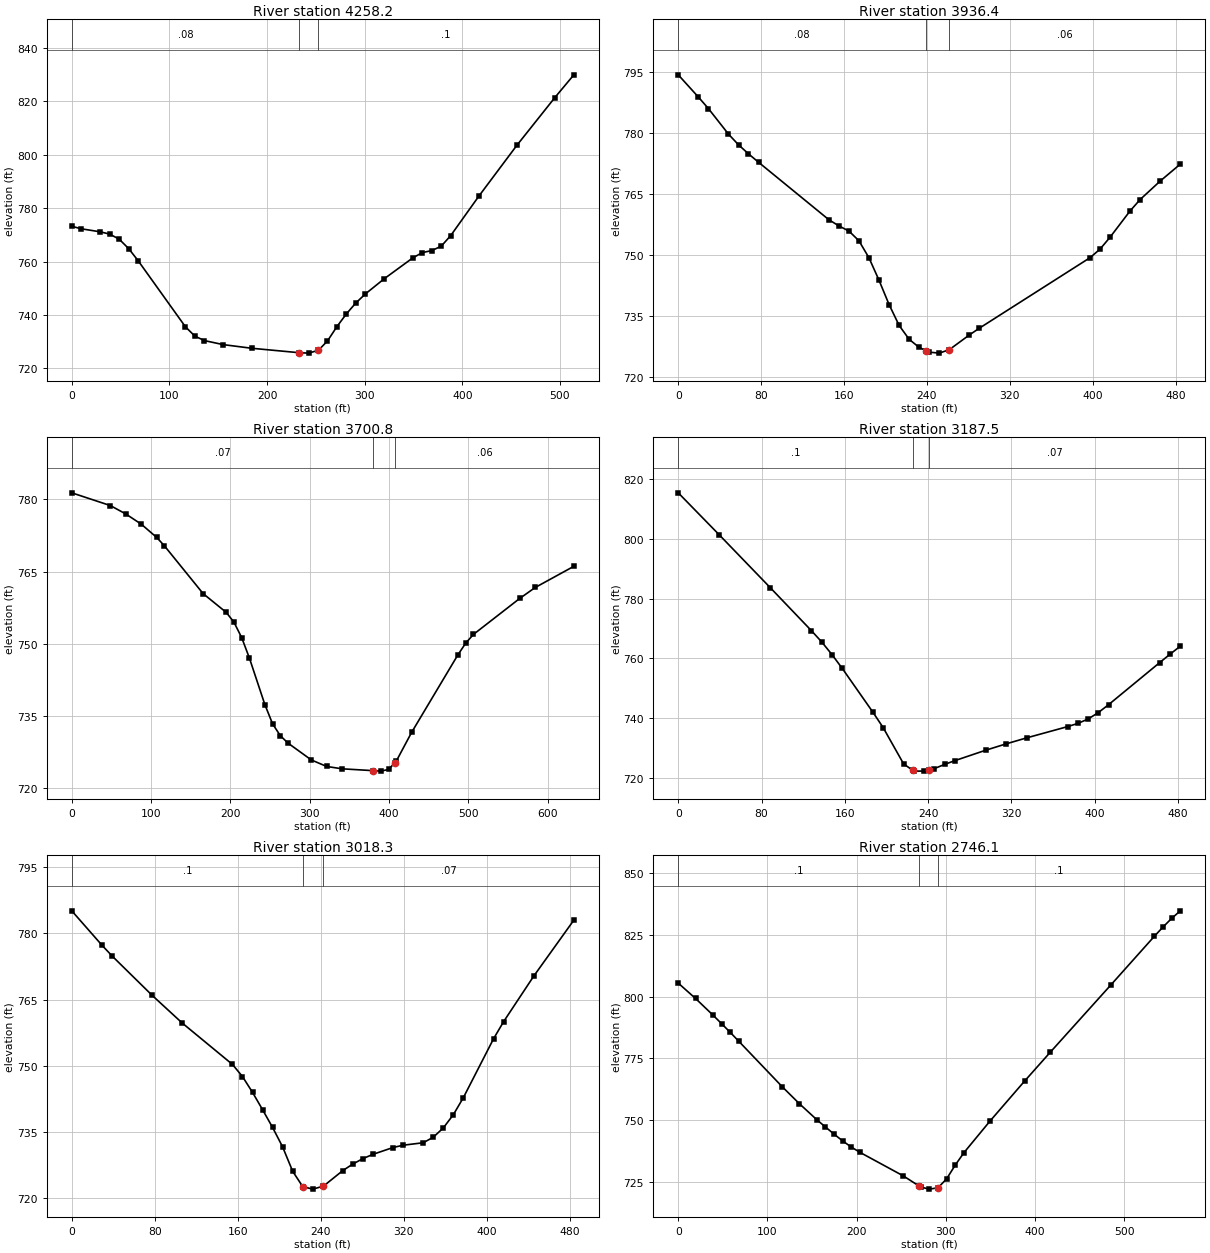
Type RM Length L Ch R = 1 ,4258.2  ,321.9,321.8,321.7
XS GIS Cut Line= 2
      1868338.13      611532.344     1867824.241      611514.983
#Sta/Elev= 30
       0  773.24     9.7   772.3    29.1  771.17    38.8  770.32    48.5  768.43
    58.2  764.91    67.9  760.38   116.4  735.59   126.1  732.09   135.8  730.43
   155.2  728.91   184.3  727.55   232.8  725.89   242.5  725.73   252.6  726.79
   261.9   730.3   271.6  735.69   281.3  740.45     291  744.55   300.8  747.93
   320.2  753.64   349.3  761.41     359  763.38   368.7  764.14   378.4  765.79
   388.1  769.76   417.2  784.67     456  803.64   494.8  821.47   514.2  829.97
#Mann= 3 , 0 , 0
       0     .08       0   232.8    .045       0   252.6      .1       0
Bank Sta=232.8,252.6
XS Rating Curve= 0 ,0
Exp/Cntr=0.3,0.1

Type RM Length L Ch R = 1 ,3936.4  ,232.8,235.5,235.5
XS GIS Cut Line= 2
     1868421.463       611221.58     1867937.088      611207.692
#Sta/Elev= 30
       0  794.33    19.4  788.88    29.1  786.04    48.5  779.75    58.2  777.12
    67.8  774.91    77.5  772.84   145.4  758.71   155.1  757.19   164.8  755.92
   174.4  753.54   184.1  749.35   193.8  743.83   203.5  737.86   213.2  732.73
   222.9  729.31   232.6  727.31   239.5  726.49   242.3  726.16     252  725.92
   261.7  726.78     281  730.39   290.7  732.06   397.4  749.37     407  751.45
   416.7  754.38   436.1  760.87   445.8  763.67   465.2  768.22   484.6  772.38
#Mann= 3 , 0 , 0
       0     .08       0   239.5    .045       0   261.7     .06       0
Bank Sta=239.5,261.7
XS Rating Curve= 0 ,0
Exp/Cntr=0.3,0.1

Type RM Length L Ch R = 1 ,3700.8  ,553.2,513.3,475.7
XS GIS Cut Line= 2
     1868488.304      611007.605     1867855.491      611027.136
#Sta/Elev= 30
       0  781.36    48.7  778.71    68.2  776.96    87.7  774.84   107.1  772.09
   116.9  770.33   165.6  760.42   194.8  756.51   204.5  754.48   214.3  751.26
     224  747.02   243.5  737.35   253.2  733.36     263  730.89   272.7  729.35
     302  725.86   321.4   724.5   340.9  724.01   379.9  723.63   389.6  723.53
   399.4  723.87   407.4  725.28   409.1  725.58   428.6   731.6     487  747.72
   496.8  750.14   506.5  751.94   564.9  759.42   584.4  761.69   633.1  766.09
#Mann= 3 , 0 , 0
       0     .07       0   379.9    .045       0   407.4     .06       0
Bank Sta=379.9,407.4
XS Rating Curve= 0 ,0
Exp/Cntr=0.3,0.1

Type RM Length L Ch R = 1 ,3187.5  ,169.6,169.2,168.8
XS GIS Cut Line= 2
     1867864.606      610531.042     1867843.772      611012.813
#Sta/Elev= 28
       0  815.46    39.4  801.37    88.6  783.58   127.9  769.24   137.8  765.46
   147.6  761.24   157.5   756.6     187  741.88   196.8  736.74   216.5  724.54
   225.5  722.36   226.4  722.14   236.2  722.16   240.5  722.53     246     723
   255.9   724.4   265.7  725.66   295.2  729.14   314.9  731.28   334.6  733.29
     374  737.07   383.8  738.14   393.6  739.61   403.5  741.78   413.3  744.42
   462.5  758.56   472.4  761.37   482.2  764.03
#Mann= 3 , 0 , 0
       0      .1       0   225.5    .045       0   240.5     .07       0
Bank Sta=225.5,240.5
XS Rating Curve= 0 ,0
Exp/Cntr=0.3,0.1

Type RM Length L Ch R = 1 ,3018.3  ,260.9,272.2,283.7
XS GIS Cut Line= 2
     1867692.152      610533.646     1867679.131      611017.587
#Sta/Elev= 30
       0  785.12      29  777.35    38.7  774.92    77.5  765.95   106.5  759.67
   154.9  750.29   164.6  747.53   174.3  743.94     184     740   193.6     736
   203.3  731.58     213  726.04   222.7  722.57   232.4     722   242.7  722.68
   261.4  726.22   271.1   727.7   280.8  728.93   290.5   729.9   309.8  731.44
   319.5  731.96   338.9  732.52   348.6  733.78   358.2  735.87   367.9  738.88
   377.6  742.76   406.7  756.11   416.3  759.96   445.4   770.3   484.1  783.01
#Mann= 3 , 0 , 0
       0      .1       0   222.7    .045       0   242.7     .07       0
Bank Sta=222.7,242.7
XS Rating Curve= 0 ,0
Exp/Cntr=0.3,0.1

Type RM Length L Ch R = 1 ,2746.1  ,365.3,371.8,377.8
XS GIS Cut Line= 2
     1867564.114      610481.563     1867279.826      610967.674
#Sta/Elev= 30
       0  805.51    19.4  799.28    38.8  792.59    48.6  789.07    58.3  785.54
      68   781.9   116.5  763.54   135.9   756.6   155.4  750.12   165.1  747.16
   174.8  744.26   184.5  741.49   194.2  739.01   203.9  736.86   252.4  727.34
   269.9  723.28   271.9  722.81   281.6  721.97   291.3   722.5     301  726.14
   310.7  731.72   320.4  736.74   349.5   749.5   388.4  765.76   417.5  777.58
   485.5  804.88     534   824.5   543.7  828.26   553.4  831.75   563.1  834.82
#Mann= 3 , 0 , 0
       0      .1       0   269.9    .045       0   291.3      .1       0
Bank Sta=269.9,291.3
XS Rating Curve= 0 ,0
Exp/Cntr=0.3,0.1