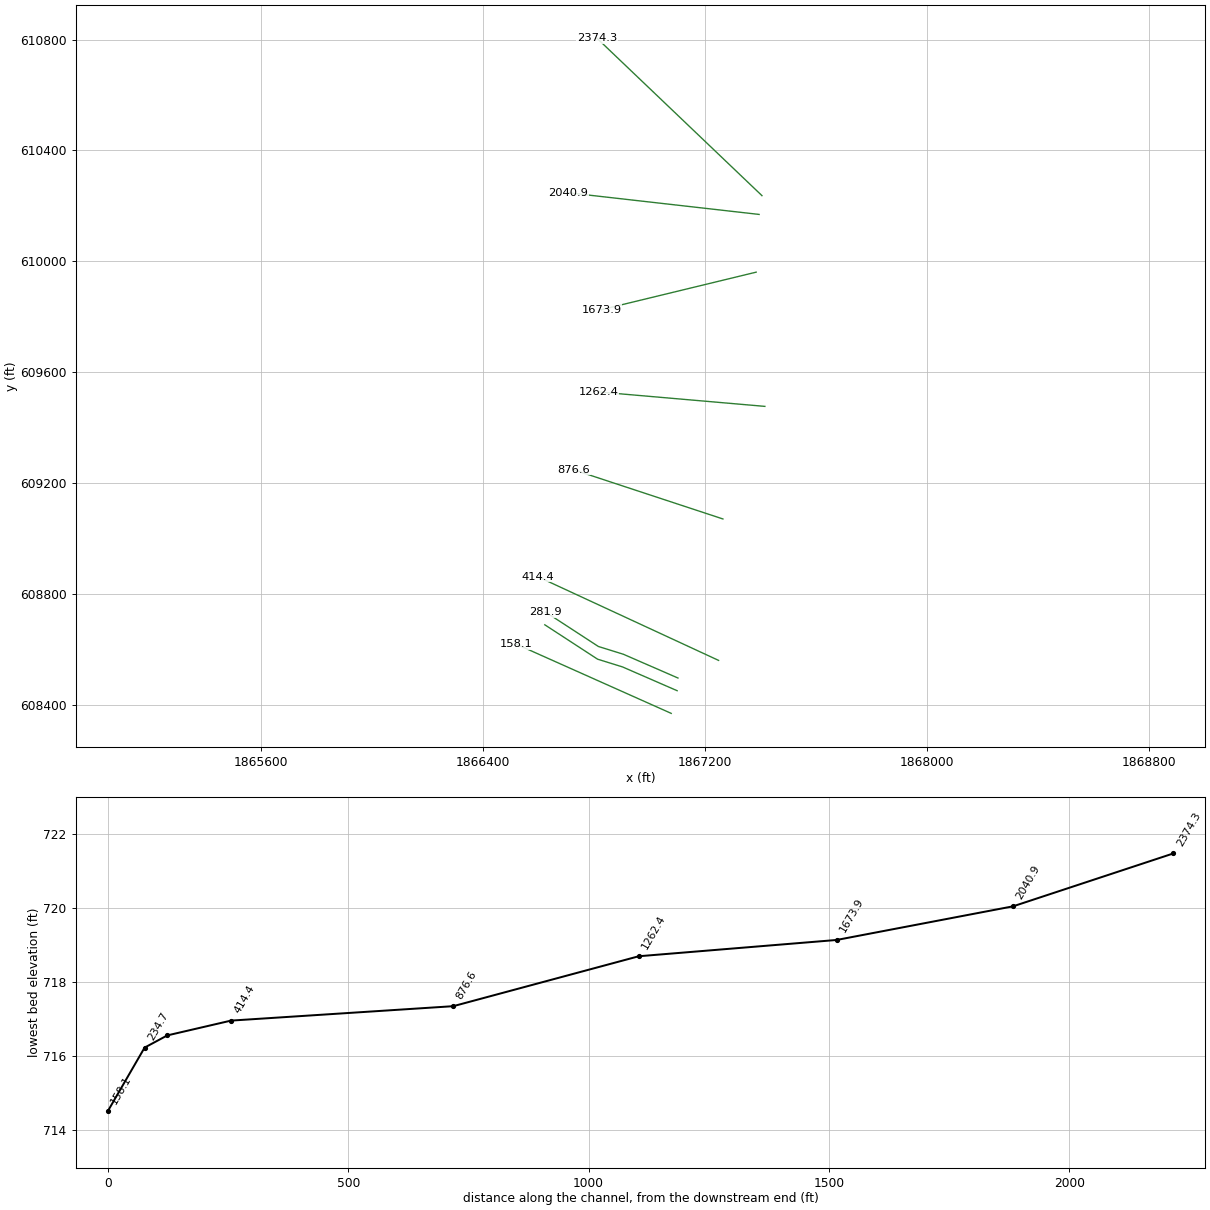
HEC-RAS study RushCreek.prj: RushCreek

--- RushCreek.g01 (geometry) --- (continued)

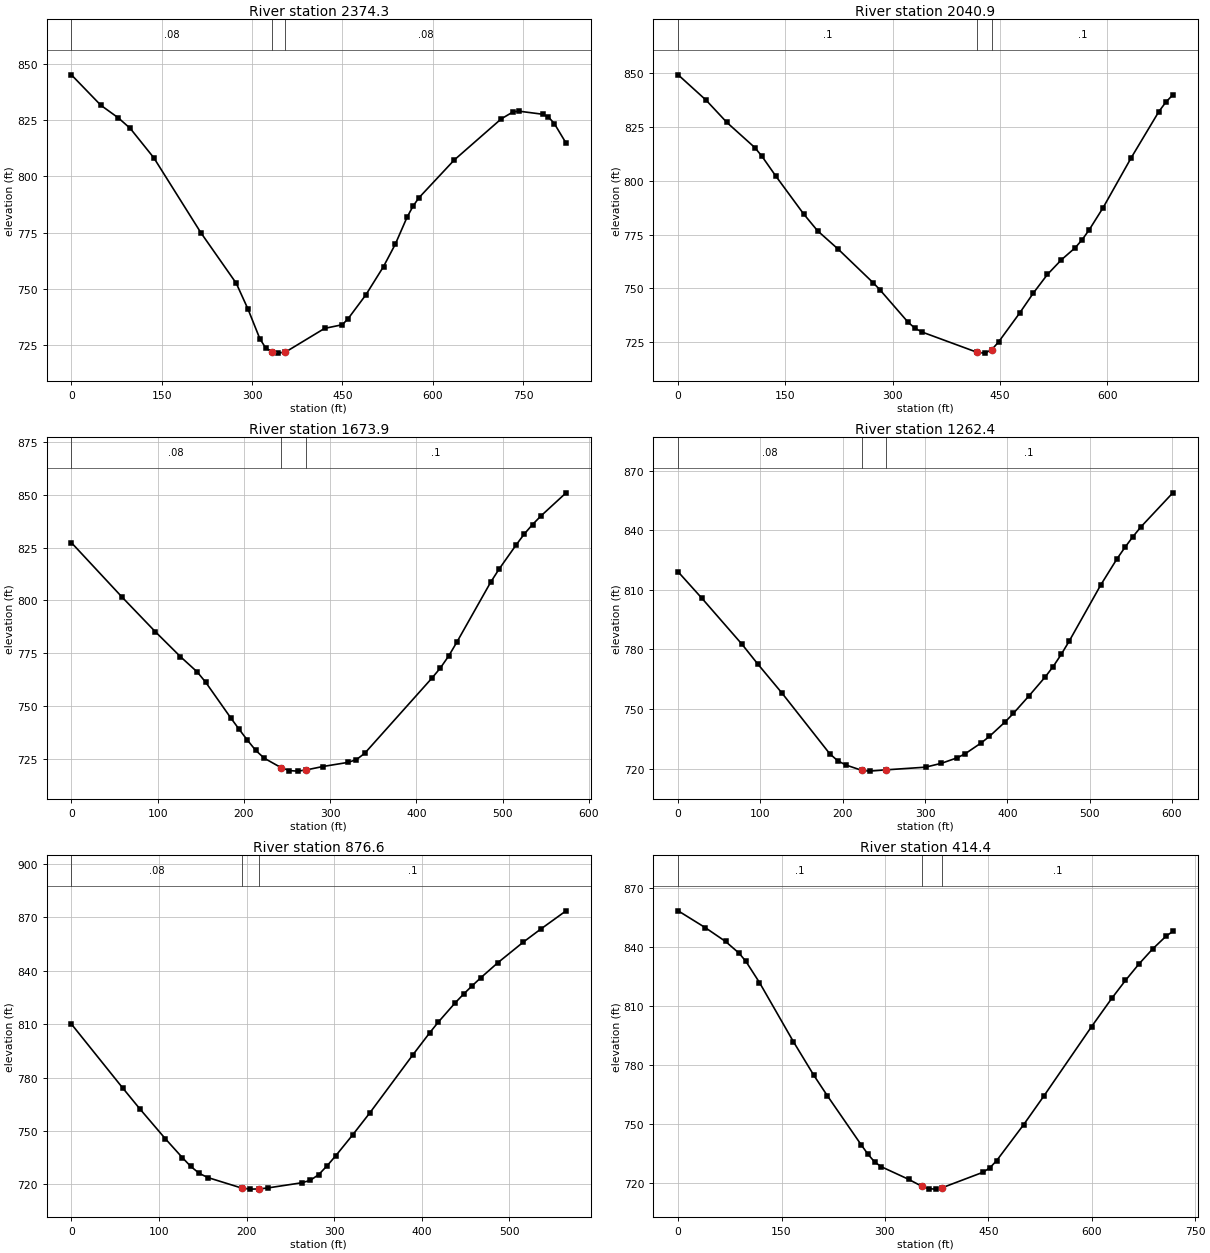
Type RM Length L Ch R = 1 ,2374.3  ,318.9,333.4,348.2
XS GIS Cut Line= 2
      1867405.26      610236.771      1866811.51       610804.48
#Sta/Elev= 30
       0  845.08    48.9  831.56    78.2  825.91    97.8  821.26   136.9  808.22
   215.2  774.88   273.8  752.49   293.4  740.95     313  727.84   322.7  723.76
   332.5  722.15   342.3  721.48   355.5  721.95   420.5  732.47   449.9  734.09
   459.6   736.8     489  747.36   518.3  759.91   537.9  769.86   557.4  781.83
   567.2  786.67     577  790.44   635.7  807.23   713.9  825.54   733.5  828.62
   743.2  828.94   782.4  827.58   792.1  826.38   801.9  823.46   821.5  814.75
#Mann= 3 , 0 , 0
       0     .08       0   332.5    .045       0   355.5     .08       0
Bank Sta=332.5,355.5
XS Rating Curve= 0 ,0
Exp/Cntr=0.3,0.1

Type RM Length L Ch R = 1 ,2040.9  ,359,367,374.9
XS GIS Cut Line= 2
     1867394.843      610169.063     1866707.343      610247.188
#Sta/Elev= 30
       0  848.98      39  837.26    68.2   826.9   107.2  815.28     117  811.33
   136.4  802.16   175.4  784.57   194.9  776.76   224.1  768.13   272.9   752.6
   282.6  749.24   321.6  734.36   331.3  731.58   341.1  729.82   418.2  720.42
   428.8  720.05   438.5  721.61   448.3  725.29   477.5  738.55     497  747.97
   516.5   756.5     536  763.28   555.5  768.92   565.2  772.66     575  777.21
   594.5  787.51   633.4  810.41   672.4  831.98   682.2  836.36   691.9   839.7
#Mann= 3 , 0 , 0
       0      .1       0   418.2    .045       0   438.5      .1       0
Bank Sta=418.2,438.5
XS Rating Curve= 0 ,0
Exp/Cntr=0.3,0.1

Type RM Length L Ch R = 1 ,1673.9  ,444,411.5,428.4
XS GIS Cut Line= 2
     1867384.426       609960.73     1866827.135      609825.313
#Sta/Elev= 30
       0  827.39    58.3  801.78    97.2  785.24   126.4  773.38   145.8  766.16
   155.5  761.36   184.7  744.39   194.4  738.99   204.1  733.78   213.8  728.93
   223.6  725.26     243  720.82   252.7  719.38   262.4  719.14   272.2   719.7
   291.6  721.33   320.8  723.29   330.5   724.6   340.2  727.65     418  763.22
   427.7  767.98   437.4  773.68   447.1  780.42     486   808.6   495.7  814.79
   515.2  826.09   524.9  831.42   534.6  835.98   544.4  840.06   573.5     851
#Mann= 3 , 0 , 0
       0     .08       0     243    .045       0   272.2      .1       0
Bank Sta=243,272.2
XS Rating Curve= 0 ,0
Exp/Cntr=0.3,0.1

Type RM Length L Ch R = 1 ,1262.4  ,390.8,385.8,380
XS GIS Cut Line= 2
     1867415.676      609476.355     1866816.718      609528.438
#Sta/Elev= 30
       0  819.04    29.1  805.63    77.6  782.57      97  772.51   126.1  758.04
   184.2  727.46   193.9  723.93   203.6  721.82     223  719.11   232.7   718.7
   252.1  719.33   300.6  720.69     320  722.65   339.4  725.45   349.1  727.52
   368.5  732.97   378.2  736.16   397.6  743.57   407.3  747.73   426.7  756.75
   446.1  766.13   455.8  771.38   465.5  777.45   475.2  784.13   513.9  812.66
   533.3  825.58     543  831.38   552.7  836.76   562.4  841.69   601.2  858.84
#Mann= 3 , 0 , 0
       0     .08       0     223    .045       0   252.1      .1       0
Bank Sta=223,252.1
XS Rating Curve= 0 ,0
Exp/Cntr=0.3,0.1

Type RM Length L Ch R = 1 ,876.6   ,465.1,462.2,459.7
XS GIS Cut Line= 2
     1867264.635      609070.105     1866728.176      609247.188
#Sta/Elev= 30
       0  810.08    58.4  774.28    77.9  762.58   107.1  745.75   126.6   735.1
   136.4  730.07   146.1  726.17   155.8  723.86   194.8   717.9   204.5  717.35
   214.3  717.47     224  717.99     263  720.92   272.7  722.25   282.5  725.55
   292.2  730.57     302  736.18   321.4  747.94   340.9  760.25   389.6  792.56
   409.1  805.12   418.8  811.06   438.3  822.01     448  826.97   457.8  831.63
   467.5  836.08     487  844.54   516.2  856.15   535.7  863.31   564.9  873.67
#Mann= 3 , 0 , 0
       0     .08       0   194.8    .045       0   214.3      .1       0
Bank Sta=194.8,214.3
XS Rating Curve= 0 ,0
Exp/Cntr=0.3,0.1

Type RM Length L Ch R = 1 ,414.4   ,129.6,132.5,135.6
XS GIS Cut Line= 2
      1867249.01      608559.688     1866597.968      608861.771
#Sta/Elev= 30
       0  858.61    39.3  850.06    68.8  843.01    88.5  837.01    98.3  832.87
     118   822.1   167.1  792.07   196.6  775.03   216.3  764.57   265.4  739.59
   275.3  734.76   285.1  730.74     295  728.31   334.3  721.96   353.9  718.34
   363.8  717.17   373.6  716.96   383.4  717.72   442.4  725.56   452.3  727.82
   462.1  731.49   501.4  749.85   530.9  764.52   599.7  799.63   629.2  814.11
   648.9  823.16   668.6  831.58   688.2  839.13   707.9  845.73   717.7  848.13
#Mann= 3 , 0 , 0
       0      .1       0   353.9    .045       0   383.4      .1       0
Bank Sta=353.9,383.4
XS Rating Curve= 0 ,0
Exp/Cntr=0.3,0.1

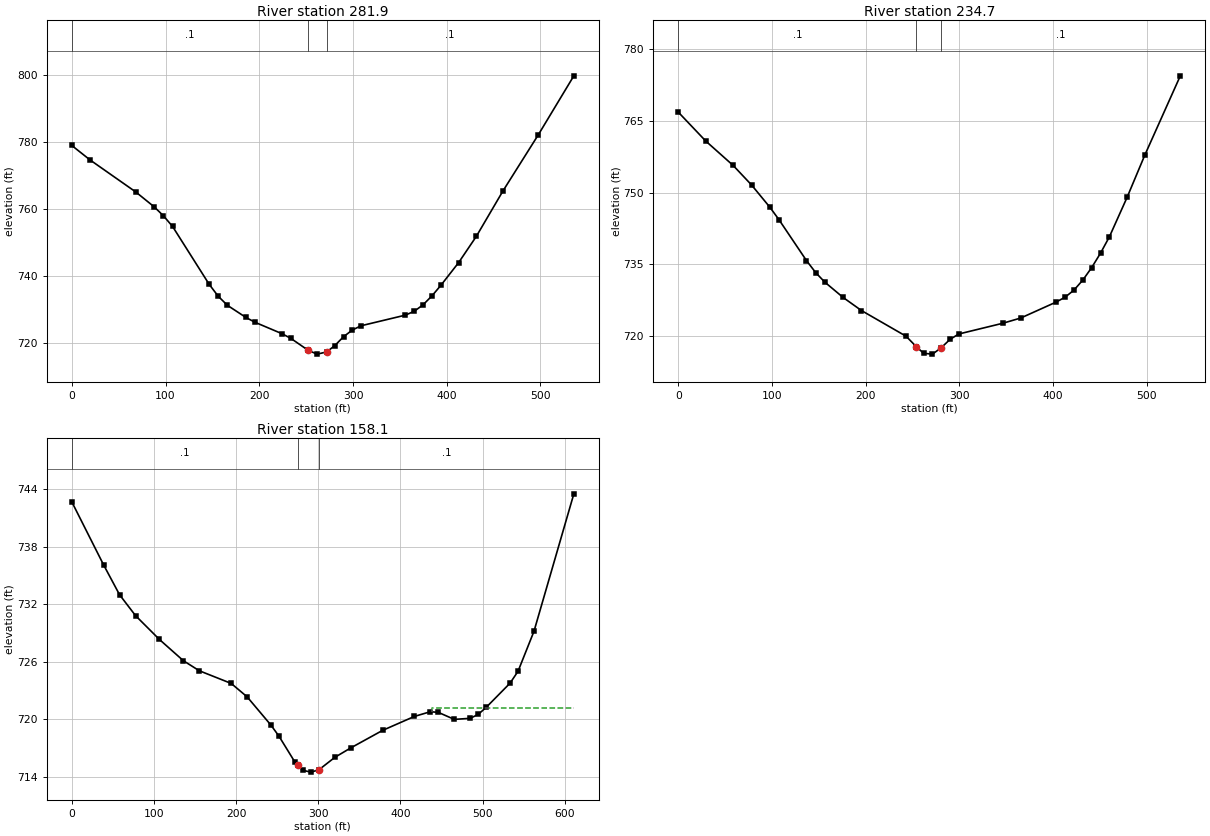
Type RM Length L Ch R = 1 ,281.9   ,46.7,47.2,46.5
XS GIS Cut Line= 4
     1867102.745      608496.112     1866905.696       608582.05
     1866816.286      608609.828     1866626.182       608733.96
#Sta/Elev= 30
       0  778.95    19.5  774.62    68.4  765.02    87.9   760.6    97.7  757.95
   107.5  754.74   146.6  737.42   156.3  733.84   166.1  731.14   185.7  727.54
   195.4  726.09   224.3  722.66   233.7  721.27   252.4  717.66   261.8  716.56
   271.8   717.2   280.5  719.09   289.9  721.76   299.2  723.75   308.6  725.04
   355.9  728.22   365.4  729.38   374.8  731.32   384.3     734   393.7  737.11
   412.7  743.93   431.6  751.78     460  765.36   497.8  782.19   535.6  799.77
#Mann= 3 , 0 , 0
       0      .1       0   252.4    .045       0   271.8      .1       0
Bank Sta=252.4,271.8
XS Rating Curve= 0 ,0
Exp/Cntr=0.3,0.1

Type RM Length L Ch R = 1 ,234.7   ,79.2,76.6,73.9
XS GIS Cut Line= 4
      1867099.75      608450.347     1866902.702      608536.285
     1866813.292      608564.062     1866623.188      608688.194
#Sta/Elev= 30
       0  766.89    29.3  760.84    58.6  755.72    78.2  751.64    97.7  746.99
   107.5  744.36   136.8  735.81   146.6   733.3   156.3  731.31   175.9  728.09
   195.4  725.36   243.1  719.97     254  717.78   261.8   716.4   271.2  716.23
   280.5  717.56   289.9  719.31   299.2  720.44   346.4   722.7   365.4  723.79
   403.2  727.13   412.7  728.15   422.1  729.62   431.6  731.73     441  734.33
   450.5  737.37     460  740.81   478.9  749.08   497.8  757.92   535.6  774.48
#Mann= 3 , 0 , 0
       0      .1       0     254    .045       0   280.5      .1       0
Bank Sta=254,280.5
XS Rating Curve= 0 ,0
Exp/Cntr=0.3,0.1

Type RM Length L Ch R = 1 ,158.1   ,158.5,158.1,157.8
XS GIS Cut Line= 2
     1867078.439      608368.508     1866520.713      608618.074
#Sta/Elev= 30
       0   742.7    38.8  736.11    58.2     733    77.6  730.83   106.7  728.34
   135.8  726.13   155.2  725.08     194  723.76   213.4  722.36   242.5   719.4
   252.2  718.25   271.6  715.55   275.4  715.22   281.3   714.7     291  714.51
   300.7  714.75   320.1  716.05   339.4  717.03   378.2  718.86     417  720.32
   436.4  720.81   446.1  720.74   465.5  720.01   484.9  720.12   494.6  720.53
   504.3  721.26   533.4  723.79   543.1  725.03   562.5   729.2     611  743.53
#Mann= 3 , 0 , 0
       0      .1       0   275.4    .045       0   300.7      .1       0
#XS Ineff= 2 , 0
                          438.35          721.19
Permanent Ineff=
       F       F
Bank Sta=275.4,300.7
XS Rating Curve= 0 ,0
Exp/Cntr=0.3,0.1

Chan Stop Cuts=-1
Use User Specified Reach Order=0
Composite Channel Slope=5